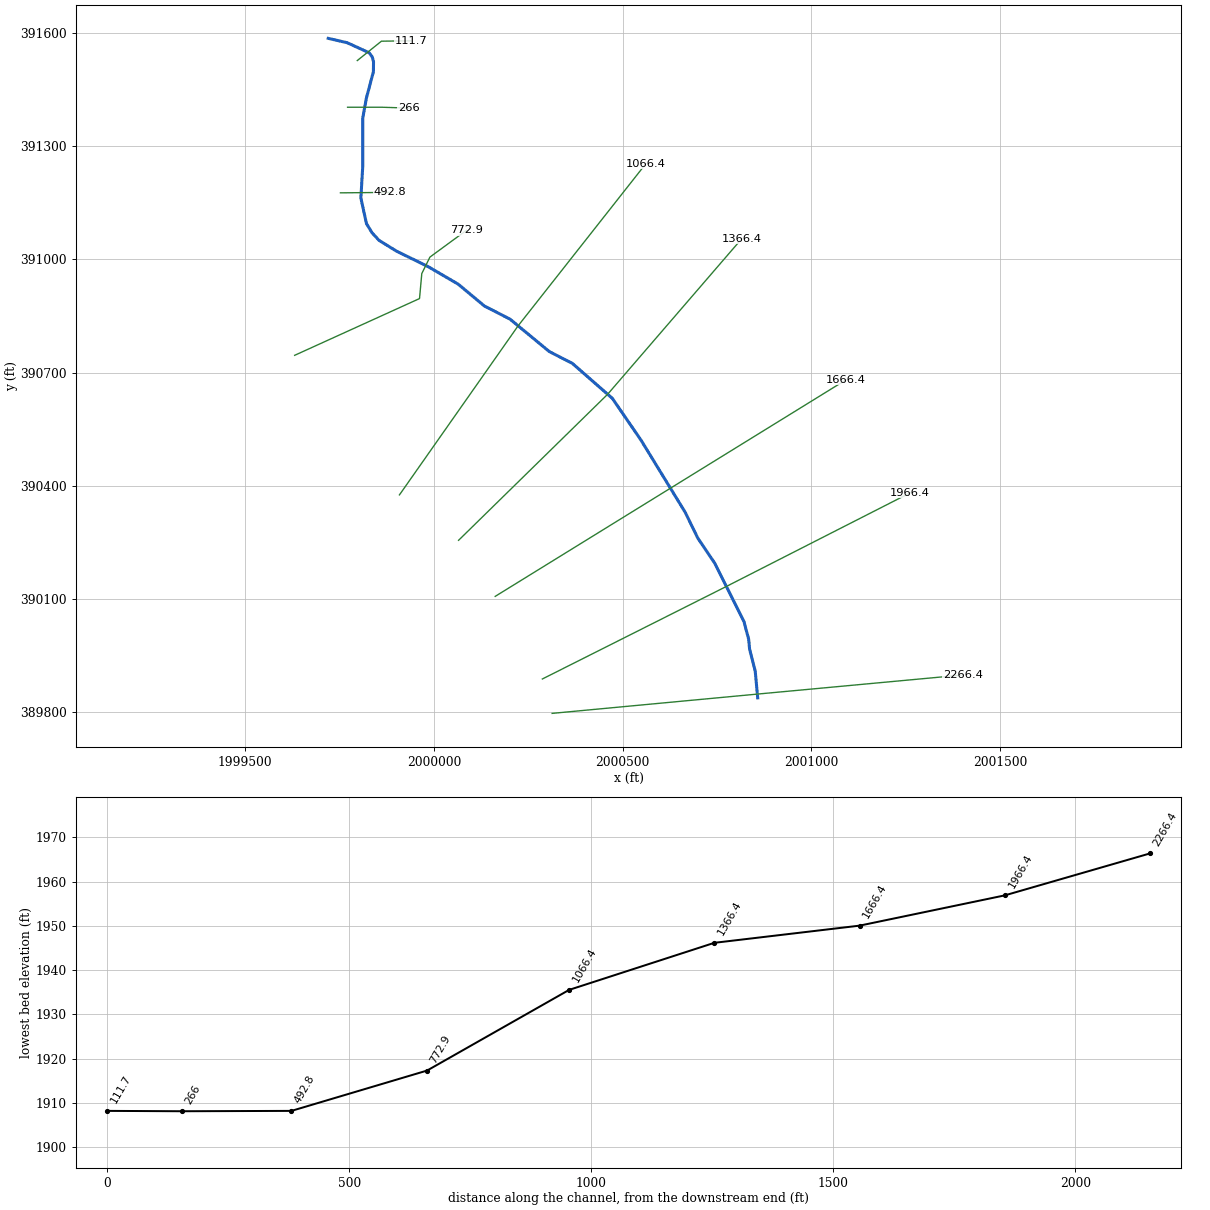
--- HaynesBrch.prj (project) ---

Proj Title=HaynesBrch
Current Plan=p01
Default Exp/Contr=0,0
English Units
Geom File=g01
Flow File=f01
Plan File=p01
BEGIN DESCRIPTION:
END DESCRIPTION:
DSS Export Rating Curves= 0
DSS Export Rating Curve Sorted= 0
DSS Export Volume Flow Curves= 0
DXF OffsetX= 0
DXF OffsetY= 0
DXF ScaleX= 0
DXF ScaleY= 0

--- HaynesBrch.p01 (plan) ---

Plan Title=Floodplain
Program Version=4.00
Geom File=g01
Flow File=f01
K Sum by GR=0
Std Step Tol=0.01
Critical Tol=0.01
Num of Std Step Trials=20
Max Error Tol=0.3
Flow Tol Ratio=0.001
Split Flow NTrial=30
Split Flow Tol=0.02
Split Flow Ratio=0.02
Log Output Level=0
Friction Slope Method=1
Unsteady Friction Slope Method=2
Unsteady Bridges Friction Slope Method=1
Global Log Level=0
CheckData=False
Run HTab=0
Run UNet=0
Run PostProcess=0
UNET Theta=0
UNET Theta Warmup=0
UNET ZTol=0
UNET ZSATol=0
UNET MxIter=0
UNET MaxInSteps=0
UNET DtIC=0
UNET DtMin=0
UNET MaxCRTS=0
UNET WFStab=0
UNET SFStab=0
UNET WFX=0
UNET SFX=0
UNET DSS MLevel=0
UNET DZMax Abort=0
UNET Convert EG Bridges=0
UNET Use Existing IB Tables=0
UNET Froude Limit=0
UNET Froude Power=0
Write IC File=0
Echo Input=False
Echo Output=False
Write Detailed=0

--- HaynesBrch.f01 (steady flow) ---

Flow Title=NFF Regression Equation
Program Version=4.00
Number of Profiles=1
Profile Names=P100yr
River Rch & RM=HaynesBrch,Main      ,2266.4
517.2105
River Rch & RM=HaynesBrch,Main      ,492.8
531.9469
Boundary for River Rch & Prof#=HaynesBrch,Main      ,1
Up Type=0
Dn Type=3
Dn Slope=0.010787

--- HaynesBrch.g01 (geometry) ---

Geom Title=USGS 3m DEM
Program Version=4.00

River Reach=HaynesBrch     ,Main
Reach XY= 30
     2000857.595      389838.516     2000850.984      389909.582
     2000836.110      389967.427     2000833.650      389993.666
     2000821.129      390040.745     2000743.558      390195.501
     2000698.935      390261.610     2000665.881      390329.371
     2000548.538      390521.085     2000472.514      390631.817
     2000366.740      390724.369     2000305.590      390755.771
     2000201.469      390841.712     2000133.708      390876.419
     2000064.294      390934.263     1999984.964      390980.540
     1999900.675      391021.857     1999854.459      391050.402
     1999835.997      391070.506     1999821.345      391094.576
     1999806.471      391162.338     1999811.429      391246.626
     1999811.429      391373.886     1999821.151      391427.354
     1999839.655      391497.088     1999839.987      391523.045
     1999836.710      391535.960     1999828.304      391547.246
     1999770.111      391573.863     1999719.910      391585.432

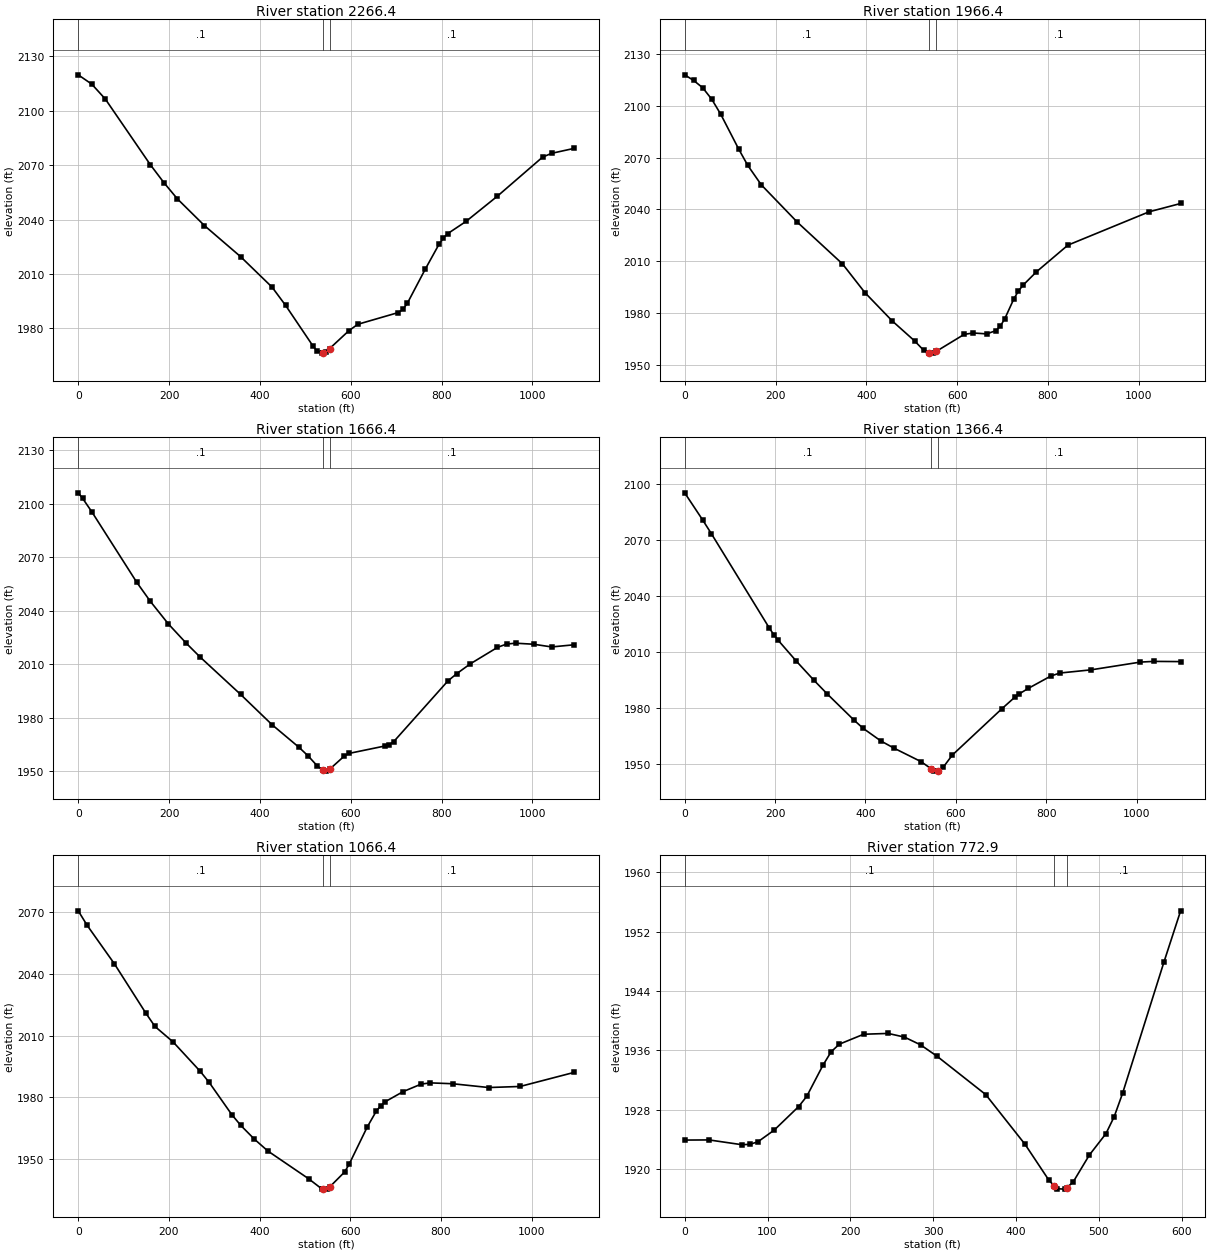
Type RM Length L Ch R = 1 ,2266.4,291.6,300,308.5
XS GIS Cut Line= 3
     2000313.063      389797.400     2000856.669      389848.473
     2001400.322      389899.045
#Sta/Elev= 30
       0 2119.87    29.8 2114.74    59.6 2106.54   158.8 2070.29   188.6 2060.42
   218.4 2051.44   278.0 2036.70   357.4 2019.60   426.9 2002.74   456.6 1992.70
   516.2 1970.56   526.2 1967.37   536.1 1966.36   538.5 1966.56   546.0 1967.19
   553.5 1968.85   595.6 1978.64   615.5 1982.26   704.8 1988.74   714.8 1990.46
   724.7 1993.86   764.4 2012.78   794.2 2026.29   804.1 2029.93   814.0 2032.34
   853.8 2038.99   923.2 2052.98  1022.5 2074.48  1042.4 2076.57  1092.0 2079.30
#Mann= 3 , 0 , 0
       0     0.1       0   538.5   0.045       0   553.5     0.1       0
Bank Sta=   538.5,   553.5
Exp/Cntr=0.3,0.1

Type RM Length L Ch R = 1 ,1966.4,298,300,301.8
XS GIS Cut Line= 3
     2000287.202      389888.469     2000775.008      390133.767
     2001261.514      390381.610
#Sta/Elev= 30
       0 2117.90    19.8 2114.64    39.7 2110.40    59.6 2103.78    79.4 2095.09
   119.1 2074.85   139.0 2065.45   168.8 2054.22   248.2 2032.60   347.5 2008.49
   397.1 1991.82   456.7 1975.58   506.3 1963.93   526.2 1958.54   538.5 1956.95
   546.0 1956.88   553.5 1957.83   615.5 1967.74   635.4 1968.53   665.1 1968.01
   685.0 1969.88   694.9 1972.43   704.8 1976.76   724.7 1988.22   734.6 1992.70
   744.6 1996.06   774.3 2003.86   843.8 2019.36  1022.5 2038.64  1092.0 2043.46
#Mann= 3 , 0 , 0
       0     0.1       0   538.5   0.045       0   553.5     0.1       0
Bank Sta=   538.5,   553.5
Exp/Cntr=0.3,0.1

Type RM Length L Ch R = 1 ,1666.4,295,300,306.9
XS GIS Cut Line= 3
     2000162.305      390107.316     2000626.916      390394.113
     2001091.527      390680.911
#Sta/Elev= 30
       0 2106.12     9.9 2102.94    29.8 2095.53   129.0 2055.90   158.8 2045.26
   198.6 2032.56   238.2 2021.69   268.0 2014.12   357.4 1993.10   426.9 1976.05
   486.4 1963.33   506.3 1958.55   526.2 1953.02   538.5 1950.56   546.0 1950.04
   553.5 1951.06   585.7 1958.45   595.6 1959.94   675.0 1964.12   685.0 1964.92
   694.9 1966.64   814.0 2000.61   833.9 2004.79   863.7 2010.27   923.2 2019.45
   943.1 2021.30   963.0 2021.79  1002.6 2021.21  1042.4 2019.69  1092.0 2020.90
#Mann= 3 , 0 , 0
       0     0.1       0   538.5   0.045       0   553.5     0.1       0
Bank Sta=   538.5,   553.5
Exp/Cntr=0.3,0.1

Type RM Length L Ch R = 1 ,1366.4,295.8,299.9,301
XS GIS Cut Line= 3
     2000065.260      390255.773     2000460.041      390642.569
     2000815.776      391055.221
#Sta/Elev= 30
       0 2095.35    39.5 2080.92    59.2 2073.40   187.5 2022.79   197.4 2019.22
   207.3 2016.19   246.7 2005.22   286.2 1994.83   315.8 1987.46   375.0 1973.44
   394.8 1969.12   434.2 1962.33   463.9 1958.39   523.1 1951.25   545.2 1947.47
   552.7 1946.22   560.2 1946.17   562.6 1946.16   572.5 1948.37   592.3 1954.77
   701.3 1979.46   731.0 1985.88   740.9 1987.65   760.7 1990.56   810.2 1997.12
   830.0 1998.74   899.4 2000.46  1008.4 2004.61  1038.1 2004.99  1097.5 2004.87
#Mann= 3 , 0 , 0
       0     0.1       0   545.2   0.045       0   560.2     0.1       0
Bank Sta=   545.2,   560.2
Exp/Cntr=0.3,0.1

Type RM Length L Ch R = 1 ,1066.4,290.1,293.5,298.2
XS GIS Cut Line= 3
     1999908.622      390376.099     2000223.361      390824.463
     2000561.070      391253.090
#Sta/Elev= 30
       0 2070.44    19.9 2063.34    79.7 2044.78   149.4 2020.74   169.3 2014.37
   209.2 2006.88   268.9 1992.67   288.8 1987.25   338.6 1971.66   358.6 1966.38
   388.4 1959.76   418.3 1953.99   508.0 1940.56   537.8 1935.53   540.3 1935.54
   547.8 1935.57   555.3 1936.77   587.5 1943.86   597.4 1947.61   637.1 1965.58
   656.9 1973.21   666.9 1975.93   676.8 1977.89   716.5 1982.81   756.2 1986.44
   776.0 1987.04   825.6 1986.62   905.0 1984.78   974.4 1985.30  1093.5 1992.12
#Mann= 3 , 0 , 0
       0     0.1       0   540.3   0.045       0   555.3     0.1       0
Bank Sta=   540.3,   555.3
Exp/Cntr=0.3,0.1

Type RM Length L Ch R = 1 ,772.9,305.1,280.1,255.1
XS GIS Cut Line= 5
     1999631.094      390745.812     1999961.820      390896.108
     1999967.838      390962.318     1999989.353      391005.953
     2000086.180      391076.960
#Sta/Elev= 30
       0 1923.91    29.4 1923.93    68.7 1923.29    78.6 1923.33    88.4 1923.68
   108.0 1925.25   137.5 1928.42   147.3 1929.80   166.9 1934.00   176.7 1935.80
   186.6 1936.83   216.0 1938.17   245.5 1938.28   265.1 1937.79   284.7 1936.74
   304.4 1935.22   363.3 1930.04   410.8 1923.33   439.5 1918.51   446.1 1917.72
   449.2 1917.35   459.0 1917.30   461.1 1917.50   468.7 1918.24   488.4 1921.90
   508.4 1924.78   518.4 1927.08   528.4 1930.19   578.5 1947.94   598.5 1954.80
#Mann= 3 , 0 , 0
       0     0.1       0   446.1   0.045       0   461.1     0.1       0
Bank Sta=   446.1,   461.1
Exp/Cntr=0.3,0.1

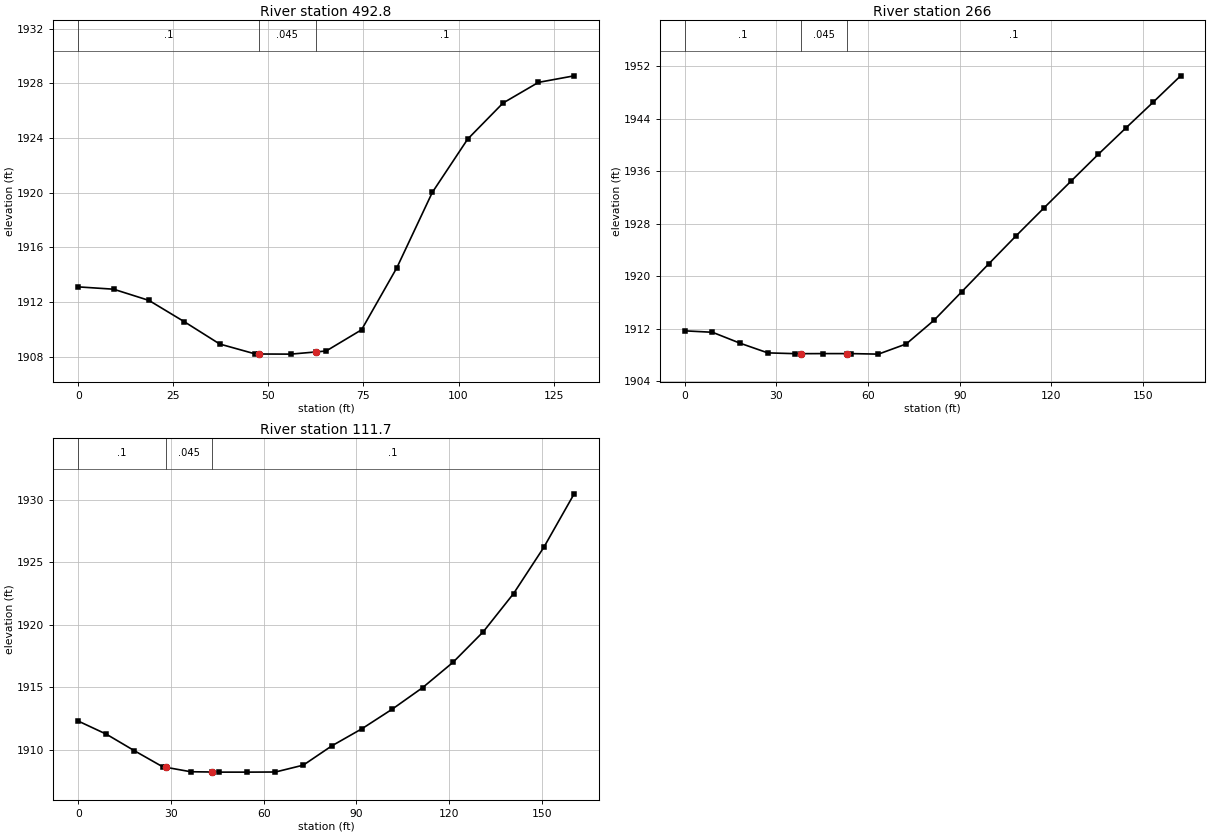
Type RM Length L Ch R = 1 ,492.8,227.1,227,226.8
XS GIS Cut Line= 2
     1999752.345      391176.201     1999882.706      391177.347
#Sta/Elev= 17
       0 1913.11     9.3 1912.94    18.6 1912.12    27.9 1910.56    37.2 1908.93
    46.6 1908.20    47.5 1908.20    55.9 1908.19    62.5 1908.35    65.2 1908.42
    74.5 1909.97    83.8 1914.52    93.1 1920.02   102.4 1923.92   111.7 1926.56
   121.0 1928.07   130.4 1928.55
#Mann= 3 , 0 , 0
       0     0.1       0    47.5   0.045       0    62.5     0.1       0
Bank Sta=    47.5,    62.5
Exp/Cntr=0.3,0.1

Type RM Length L Ch R = 1 ,266,138.7,153.6,168.7
XS GIS Cut Line= 3
     1999771.243      391402.884     1999861.856      391402.933
     1999933.516      391400.684
#Sta/Elev= 21
       0 1911.66     9.1 1911.44    18.1 1909.78    27.2 1908.30    36.2 1908.18
      38 1908.18    45.3 1908.19      53 1908.19    54.4 1908.19    63.4 1908.11
    72.5 1909.66    81.6 1913.27    90.6 1917.58    99.6 1921.91   108.5 1926.16
   117.5 1930.35   126.5 1934.50   135.4 1938.58   144.4 1942.58   153.4 1946.54
   162.3 1950.52
#Mann= 3 , 0 , 0
       0     0.1       0      38   0.045       0      53     0.1       0
Bank Sta=      38,      53
Exp/Cntr=0.3,0.1

Type RM Length L Ch R = 1 ,111.7,95.8,111.6,127.2
XS GIS Cut Line= 3
     1999796.990      391526.559     1999860.896      391577.877
     1999939.326      391578.846
#Sta/Elev= 20
       0 1912.28     9.1 1911.23    18.2 1909.90    27.3 1908.62    28.3 1908.58
    36.4 1908.22    43.3 1908.20    45.5 1908.19    54.6 1908.19    63.8 1908.20
    72.8 1908.75    82.0 1910.29    91.8 1911.67   101.6 1913.24   111.4 1914.96
   121.2 1916.98   131.0 1919.43   140.8 1922.49   150.6 1926.20   160.4 1930.48
#Mann= 3 , 0 , 0
       0     0.1       0    28.3   0.045       0    43.3     0.1       0
Bank Sta=    28.3,    43.3
Exp/Cntr=0.3,0.1